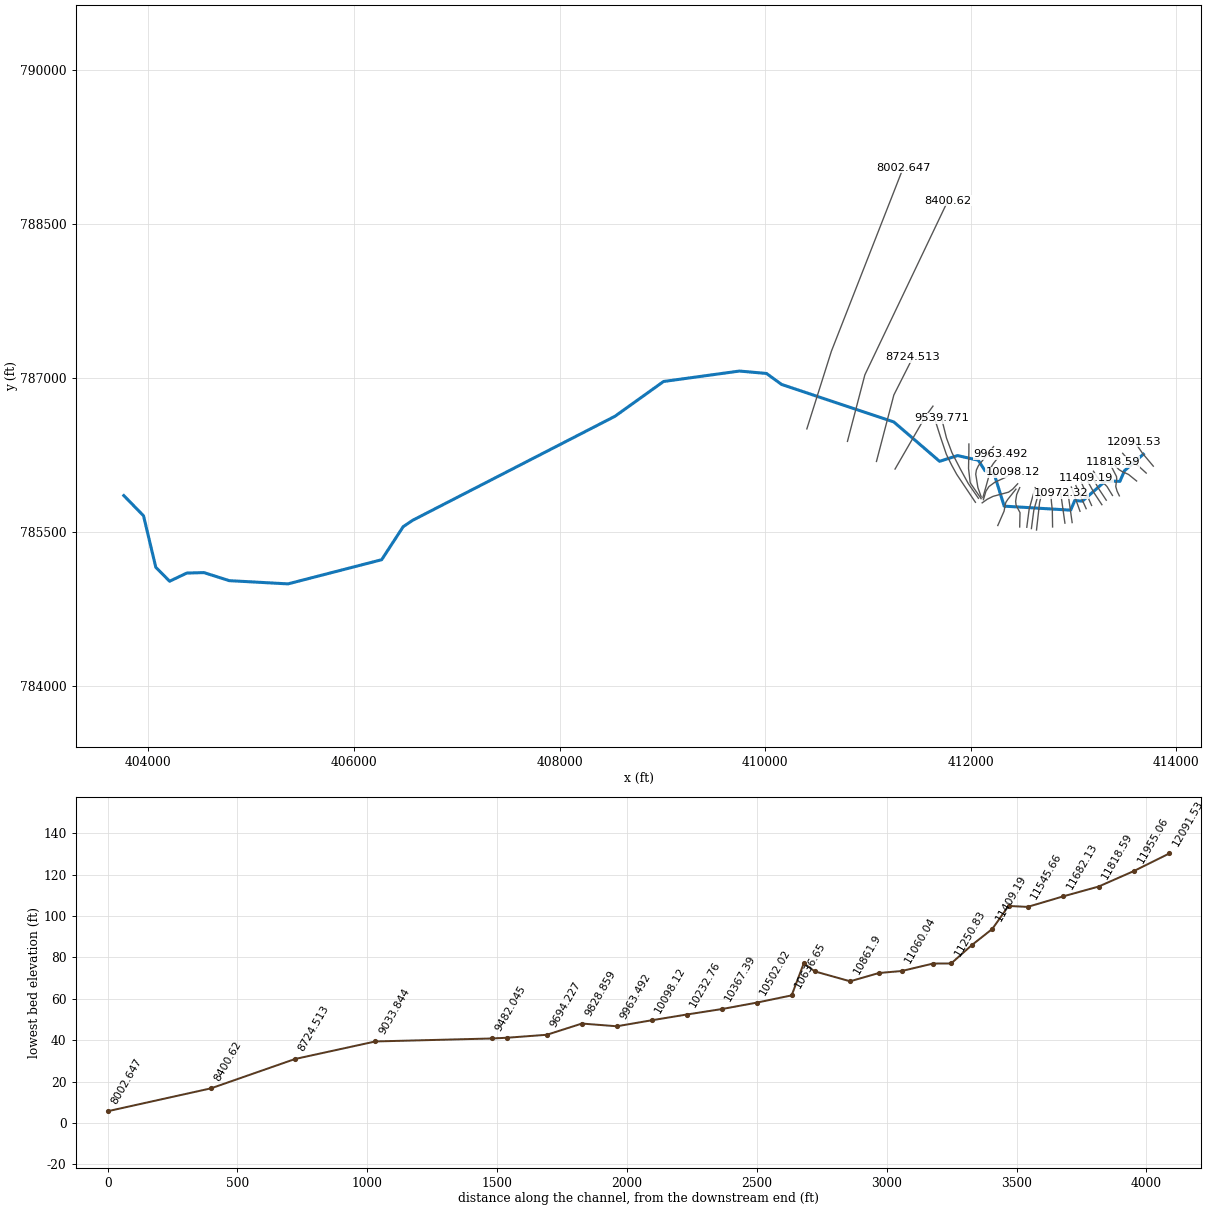
--- 3716_ras.prj (project) ---

Proj Title=3716
Current Plan=p01
Default Exp/Contr=0.3,0.1
English Units
Geom File=g01
Flow File=f01
Plan File=p01
Y Axis Title=Elevation
X Axis Title(PF)=Main Channel Distance
X Axis Title(XS)=Station
BEGIN DESCRIPTION:
RFD model 3716 exported to HEC-RAS
END DESCRIPTION:

--- 3716_ras.p01 (plan) ---

Plan Title=Plan 01
Program Version=4.10
Short Identifier=Plan 01
Geom File=g01
Flow File=f01
Subcritical Flow
Calc Critical at every XS
Secant Critical Depth

--- 3716_ras.f01 (steady flow) ---

Flow Title=Flow 01
Program Version=5.01
Number of Profiles= 6
Profile Names=10yr,25yr,50yr,100yr,100plus,500yr
River Rch & RM=3716,38,12091.53
  173.21  277.87  375.77  465.49  679.62 1180.49
River Rch & RM=3716,38,11955.06
  175.97  282.34  381.84  473.03  690.63 1197.01
River Rch & RM=3716,38,11818.59
  177.93  285.51  386.15   478.4  698.46 1208.76
River Rch & RM=3716,38,11682.13
  182.21  292.43  395.58  490.13  715.59 1234.46
River Rch & RM=3716,38,11545.66
   185.7  298.08  403.27   499.7  729.56 1255.33
River Rch & RM=3716,38, 11471.9
  189.93  304.93  412.61  511.33  746.54 1280.65
River Rch & RM=3716,38,11331.43
  193.72   311.1  421.02  521.82  761.85  1303.5
River Rch & RM=3716,38,11181.12
  195.62  314.18  425.22  527.05   769.5 1314.87
River Rch & RM=3716,38,10972.32
  200.87  322.71  436.88   541.6  790.74 1346.49
River Rch & RM=3716,38, 10861.9
  204.21  328.15  444.32  550.89  804.31 1366.66
River Rch & RM=3716,38,10725.43
  206.82   332.4  450.12  558.13  814.87 1382.28
River Rch & RM=3716,38,10636.65
  212.82  342.13  463.38  574.64  838.98  1417.7
River Rch & RM=3716,38,10502.02
  215.41  346.34  469.13  581.82  849.45 1433.09
River Rch & RM=3716,38,10367.39
  216.51  348.13  471.58  584.88  853.92 1439.67
River Rch & RM=3716,38,10232.76
  219.82  353.52  478.93  594.05  867.32 1459.33
River Rch & RM=3716,38,10098.12
  229.47  369.16  500.24  620.58  906.04 1515.54
River Rch & RM=3716,38,9963.492
   232.4  373.91  506.73  628.66  917.85 1532.67
River Rch & RM=3716,38,9828.859
  237.17  381.64  517.27  641.79  937.01 1560.36
River Rch & RM=3716,38,9694.227
  243.35  391.68  530.96  658.85  961.93 1596.27
River Rch & RM=3716,38,9539.771
  248.38  399.86  542.13  672.79  982.28  1625.6
River Rch & RM=3716,38,9033.844
  268.66  432.84   587.2  729.01 1064.35 1742.98
River Rch & RM=3716,38,8724.513
   279.9  451.13  612.18  760.18 1109.86 1807.52
River Rch & RM=3716,38, 8400.62
  289.66  467.01  633.87  787.25 1149.38 1863.26
River Rch & RM=3716,38,8002.647
  298.31  481.08  653.11  811.26 1184.43 1912.48
River Rch & RM=3716,38,7589.689
  306.83  494.98  672.14  835.03 1219.15 1961.21
River Rch & RM=3716,38,6815.682
     321  518.11  703.82  874.64 1276.97 2042.03
River Rch & RM=3716,38,5846.538
  332.03  536.13  728.51   905.5 1322.04 2104.65
Boundary for River Rch & Prof#=3716,38,1
Up Type= 0
Dn Type= 2
Boundary for River Rch & Prof#=3716,38,2
Up Type= 0
Dn Type= 2
Boundary for River Rch & Prof#=3716,38,2
Up Type= 0
Dn Type= 2
Boundary for River Rch & Prof#=3716,38,2
Up Type= 0
Dn Type= 2
Boundary for River Rch & Prof#=3716,38,2
Up Type= 0
Dn Type= 2
Boundary for River Rch & Prof#=3716,38,2
Up Type= 0
Dn Type= 2

--- 3716_ras.g01 (geometry) ---

Geom Title=3716
Program Version=4.10

River Reach=3716,38
Reach XY= 30
413679.336695194 786258.80626981413494.961695194 786097.86876981
413451.211695194 785994.74376981413310.586695194785998.389603123
413085.586695284785802.035436481413011.628361881785808.285436481
412972.045028538785714.535436481412325.170028538785753.597936481
412226.211695194 786072.86876981412138.711695194 786097.86876981
412073.086695194786200.472936481411871.524195284786245.264603138
411697.045028538786189.535436481411251.732528538786572.347936466
410160.586695194786936.931269795410013.169801772787044.031282619
409750.324527055787067.537770614409012.007108957786966.032481596
408539.878597885786627.823317274406571.545264572785615.739983931
406479.461931407785553.656650662 406270.29526493785232.406650618
405359.045264572784997.406650618404787.795264721785028.795539528
404541.684153855785107.128872856404375.017486781785102.684428468
404207.795264572785023.239983946404073.559153557785158.101095065
403953.906375676 785659.83720617403762.170264721785856.469150633

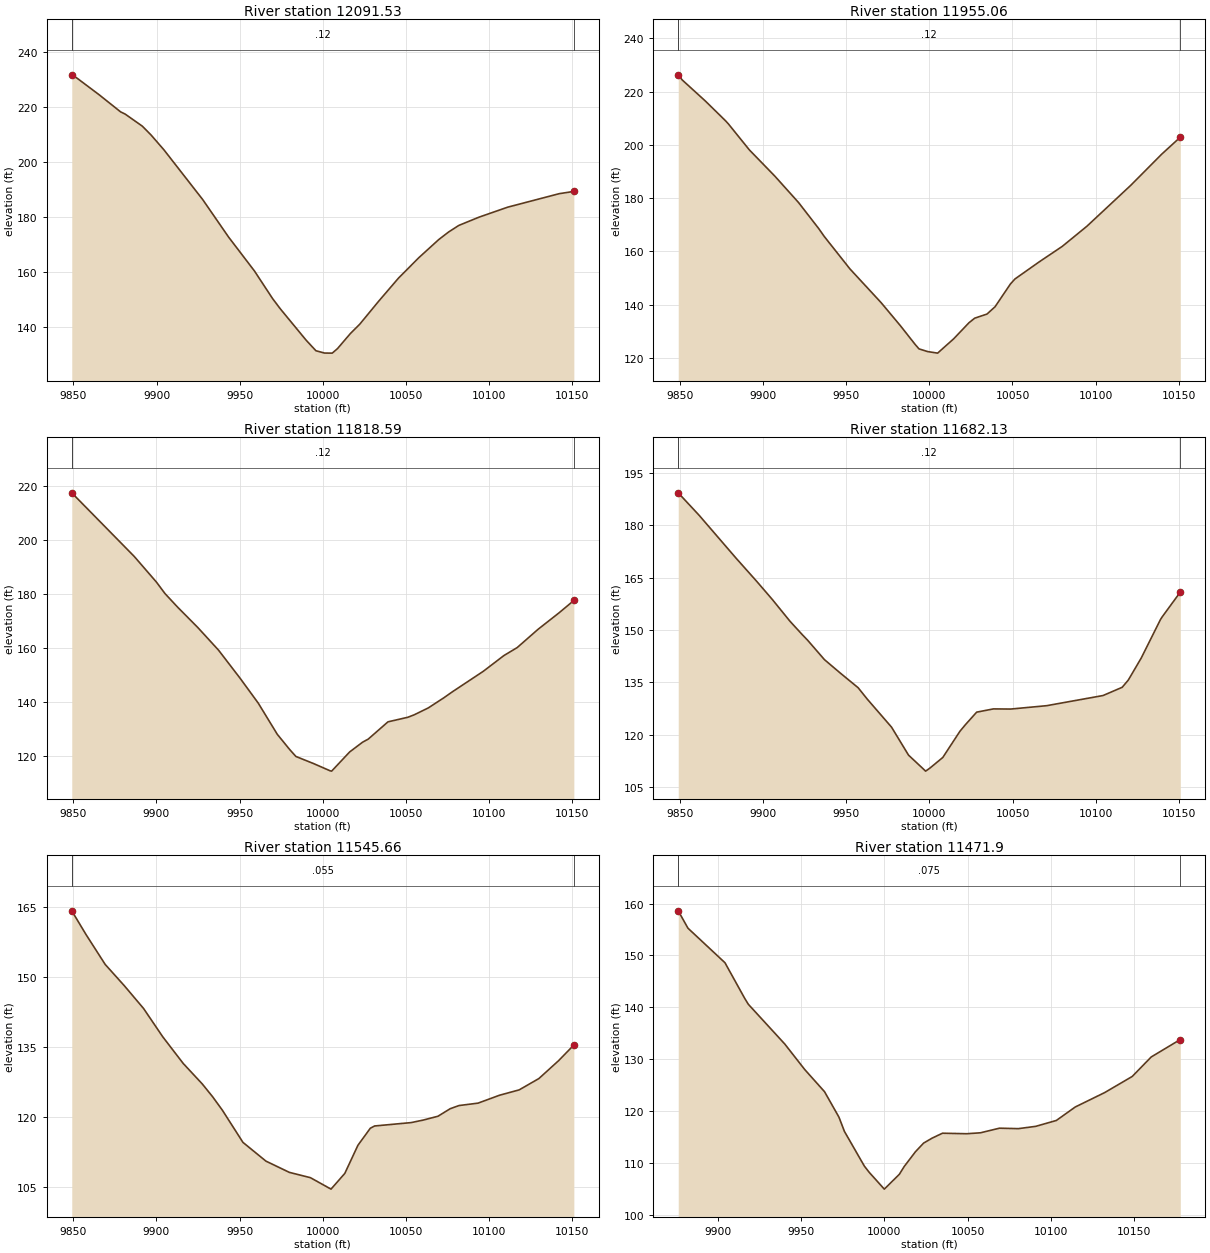
Type RM Length L Ch R = 1 ,12091.53,136.466700,136.466700,136.466700
XS GIS Cut Line= 5
413775.628973689786142.501217209413679.217846096786257.397059076
413677.927484461786258.925118907413668.133912196786271.097803535
413592.656361096786382.253695415
#Sta/Elev= 30
9849.013231.84799852.275230.58999865.548224.54159878.383218.33619881.105217.5311
9891.437213.12279896.662209.91749904.492 204.4469927.777186.32369943.334172.6505
9958.891160.27359969.762150.23499974.448146.45779990.005135.00349995.871 131.173
   10001130.335910005.67130.3057 10008.8131.931310016.62137.4774 10022.2140.8484
10033.43 149.12510045.52157.6761 10057.8165.156110069.69171.716910075.61174.4836
10081.78176.892710093.87179.898810111.21183.561810142.21188.488210150.98189.3054
#Mann= 3 , 0 , 0
9849.013    0.12       09849.013    0.12       010150.98    0.12       0
#XS Ineff= 2 , 0
       0                               0
Bank Sta=9849.013,10150.98
Exp/Cntr=0.3,0.1

Type RM Length L Ch R = 1 ,11955.06,136.466700,136.466700,136.466700
XS GIS Cut Line= 6
413706.704827943786075.224092631413630.577569276 786145.12590934
413567.810127364786178.769410512413547.466922835786193.080497578
413513.966405056 786225.38275595413477.690659646786267.568854561
#Sta/Elev= 30
9849.053226.33759851.429224.42399865.365216.49699877.446209.10799879.301207.8367
9891.803198.14739907.174188.26589921.423178.34179933.512 168.5979936.844165.6303
9952.264153.45349971.039140.76099982.704132.03999991.472125.08629993.787123.4094
    9999122.3911   10005121.810310014.69127.208810023.86133.228710027.29134.9392
10034.68 136.48510039.52139.221310048.73147.752810051.49149.6599 10065.9156.0124
10079.94161.909410094.71169.448610121.14184.853410139.69196.5194 10150.9202.9217
#Mann= 3 , 0 , 0
9849.053    0.12       09849.053    0.12       0 10150.9    0.12       0
#XS Ineff= 2 , 0
       0                               0
Bank Sta=9849.053,10150.9
Exp/Cntr=0.3,0.1

Type RM Length L Ch R = 1 ,11818.59,136.466700,136.466700,136.466700
XS GIS Cut Line= 6
413613.191272295785998.184035629413534.570209844786061.718135088
413467.858073682 786092.50806052413441.805189581786109.322895503
413412.425858653786138.711279972413379.782195995786182.254443419
#Sta/Elev= 30
9849.068217.49029886.606193.91089899.922184.41799905.097180.14289912.501175.2231
9924.906167.49549937.311159.13469950.249148.7361 9961.18139.49529972.602127.9503
9980.102122.26689983.791119.72549994.535117.053910004.35114.413210005.29114.2819
10016.12121.393710023.86124.998510027.26126.144110039.16132.559210051.06134.2508
10054.87  135.1510063.38137.719410072.71141.463110077.88143.704410096.47151.3099
10108.85157.140610116.83160.096310129.33166.855610141.82172.900410150.89177.5641
#Mann= 3 , 0 , 0
9849.068    0.12       09849.068    0.12       010150.89    0.12       0
#XS Ineff= 2 , 0
       0                               0
Bank Sta=9849.068,10150.89
Exp/Cntr=0.3,0.1

Type RM Length L Ch R = 1 ,11682.13,136.466700,136.466700,136.466700
XS GIS Cut Line= 6
413445.277306699785853.720918592413423.064977423785900.272692986
413410.630266557785944.361637915413419.904349283786018.279173295
413417.582122063786041.828123858413369.588061061786135.403591107
#Sta/Elev= 30
9849.115189.28379861.612182.87819883.772170.61169896.201163.95719905.695158.6975
9916.274152.48279923.679148.62939926.752147.10979936.992141.47539946.579137.6048
9957.257133.41759962.728130.15549977.292122.13999987.528114.10869997.789 109.531
10000.35110.390910008.11113.447910018.37120.929210021.74122.859910028.46126.4342
10038.54127.361510048.92127.319310070.53128.284710104.42131.196310115.91133.5535
10119.55135.6011 10127.4141.974210138.89152.936210139.86153.677310150.84160.8423
#Mann= 3 , 0 , 0
9849.115    0.12       09849.115    0.12       010150.84    0.12       0
#XS Ineff= 2 , 0
       0                               0
Bank Sta=9849.115,10150.84
Exp/Cntr=0.3,0.1

Type RM Length L Ch R = 1 ,11545.66,73.764100,73.764100,73.764100
XS GIS Cut Line= 6
 413378.60229752785857.609482965413325.795044436785943.552082775
413307.949672051785962.637846994 413249.35918795786012.249586687
413224.743582746786044.044121484413194.045847266786092.796137592
#Sta/Elev= 30
9849.068164.12859857.604 159.0669869.154152.64019880.703148.05479892.253143.1803
9903.802137.10169916.106131.38869927.496127.02349933.759124.2593 9939.63121.3714
 9951.99114.47769965.814110.45869979.874108.05089992.545106.910310004.93104.4561
10013.23107.829810021.09113.847610028.55117.506310031.12117.9964 10053.1118.7207
10060.22119.249210069.23120.083810076.56121.694210081.87122.376210093.31122.8915
10106.26124.590610118.08125.740910129.89128.162410141.71131.984210150.92 135.354
#Mann= 3 , 0 , 0
9849.068   0.055       09849.068   0.055       010150.92   0.055       0
#XS Ineff= 2 , 0
       0                               0
Bank Sta=9849.068,10150.92
Exp/Cntr=0.3,0.1

Type RM Length L Ch R = 1 , 11471.9,62.702600,62.702600,62.702600
XS GIS Cut Line= 5
 413318.22149182785811.539405028413239.642742761785930.663955266
 413236.21018493785937.090011536413235.367962318785938.904029472
413163.089666732 786070.32868757
#Sta/Elev= 30
9875.996158.59979881.847155.24919904.101148.58739916.081141.65619918.169140.5658
 9940.04132.9169 9952.02128.0058    9964123.70319972.652118.80269975.979116.0321
9987.959109.34639990.813108.17029999.938104.910710008.97107.764810011.92 109.279
 10018.7112.133710023.62113.801310028.75 114.75610034.95115.6974 10049.5115.5967
10057.77115.778210069.18116.6645 10080.6116.579810091.01117.021310103.42118.1579
10114.83120.762310132.51123.538210149.07126.648710160.48130.405510177.98133.7709
#Mann= 3 , 0 , 0
9875.996   0.075       09875.996   0.075       010177.98   0.075       0
#XS Ineff= 2 , 0
       0                               0
Bank Sta=9875.996,10177.98
Exp/Cntr=0.3,0.1

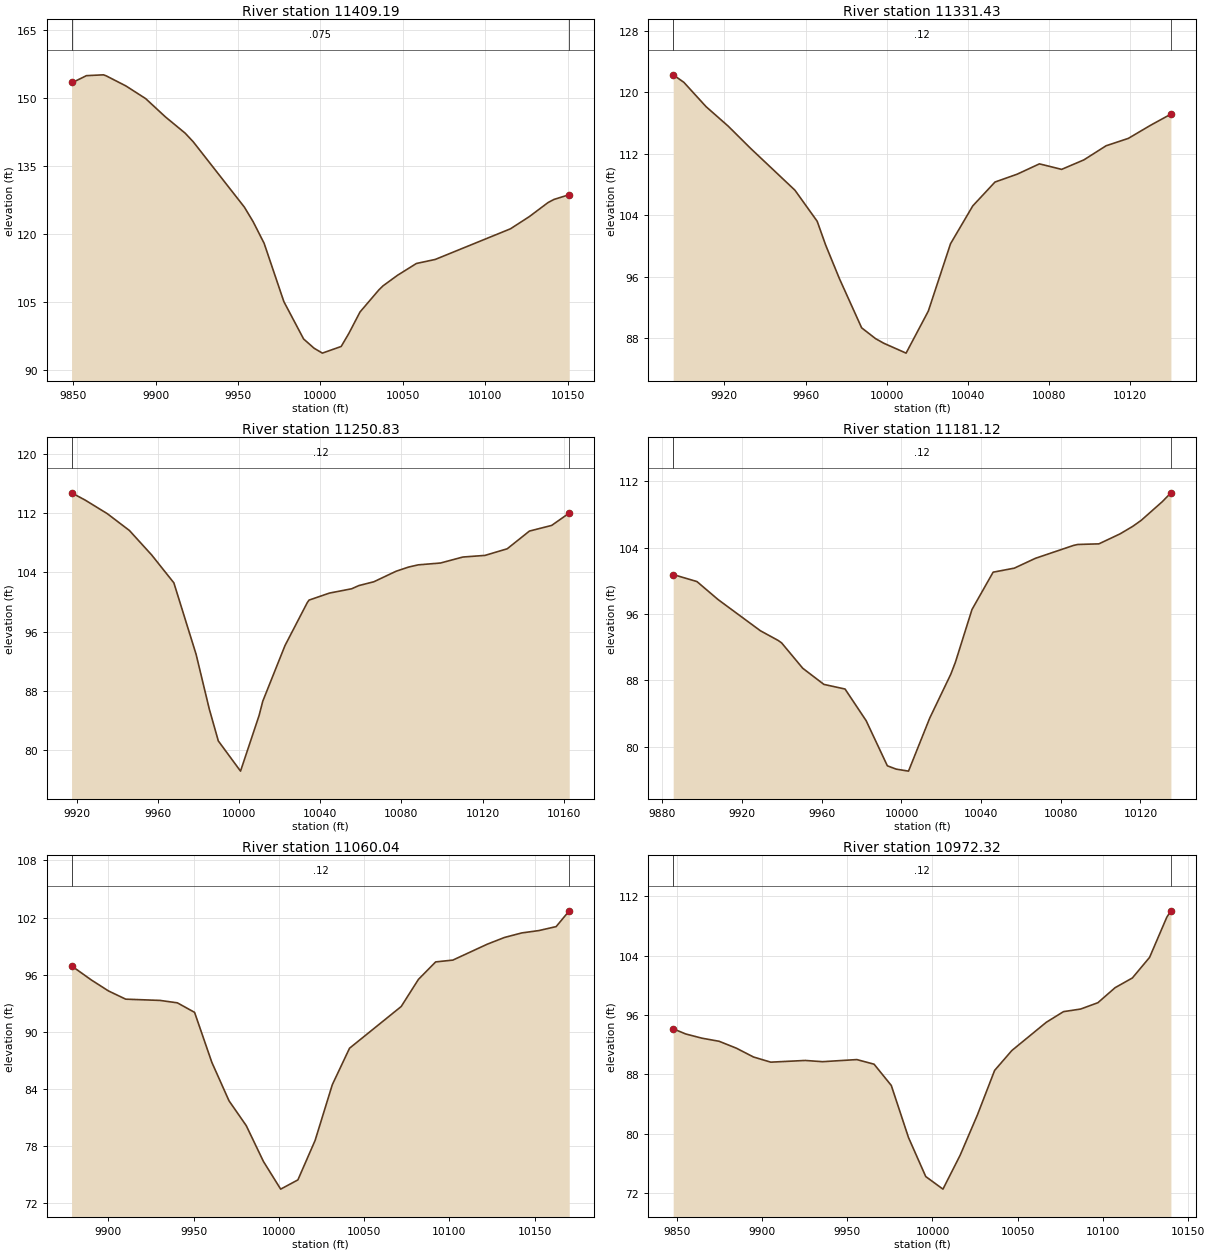
Type RM Length L Ch R = 1 ,11409.19,77.766100,77.766100,77.766100
XS GIS Cut Line= 5
413275.667995997785767.466141497413197.089246937785886.590691734
413193.656689106785893.016748005413192.814466495785894.830765941
413120.536170909786026.255424039
#Sta/Elev= 30
9849.008 153.5199850.221153.52429858.033154.92829868.382155.11159870.013154.8908
9881.992152.66199893.972149.87069905.952145.84299917.931 142.2599922.865140.3434
 9953.87125.95689959.187122.7471 9965.85 117.9889977.829105.13059989.80996.89862
9996.14994.8660410001.1993.7803810012.61 95.250710017.2298.0973710024.02102.8381
10035.43107.695710037.97108.599510046.84110.948410058.26113.537210069.67 114.424
10115.32121.177510126.73123.857210138.14126.965910141.73127.651810150.99128.7016
#Mann= 3 , 0 , 0
9849.008   0.075       09849.008   0.075       010150.99   0.075       0
#XS Ineff= 2 , 0
       0                               0
Bank Sta=9849.008,10150.99
Exp/Cntr=0.3,0.1

Type RM Length L Ch R = 1 ,11331.43,80.596600,80.596600,80.596600
XS GIS Cut Line= 2
413175.579423749 785760.20784986413075.753034824785984.166183189
#Sta/Elev= 25
9894.771122.27129900.017121.29739910.966 118.1329921.914115.58659932.863112.7168
 9954.76107.26489965.708103.22959969.882100.13379976.65695.771979987.60589.37671
9994.44487.974439998.55387.36589 10009.586.0862310020.4591.54963 10031.4100.3091
10042.35105.2277 10053.3108.330910064.24109.353310075.19110.694710086.14109.9778
10097.09111.211210108.04113.047110118.99114.006510129.93  115.7110139.97117.1605
#Mann= 3 , 0 , 0
9894.771    0.12       09894.771    0.12       010139.97    0.12       0
#XS Ineff= 2 , 0
       0                               0
Bank Sta=9894.771,10139.97
Exp/Cntr=0.3,0.1

Type RM Length L Ch R = 1 ,11250.83,69.707200,69.707200,69.707200
XS GIS Cut Line= 2
 413122.62803486 785728.95784986413022.801645935785952.916183189
#Sta/Elev= 29
 9917.52114.78179924.135113.81349935.083111.96979946.032109.6843 9956.98106.3756
9967.929102.59939978.87792.931419985.38185.517919989.82681.2055310000.7777.11893
10009.9484.6713310011.7286.5742210022.6794.1073410033.62 99.907410034.51100.2625
10044.57101.212710055.52101.797310059.07102.229710066.46102.746510077.41104.1701
10083.63104.740410088.36105.034410099.31105.283310110.26106.090310121.21106.3132
10132.16107.2081 10143.1109.606210154.05110.369810162.72112.0424
#Mann= 3 , 0 , 0
 9917.52    0.12       0 9917.52    0.12       010162.72    0.12       0
#XS Ineff= 2 , 0
       0                               0
Bank Sta=9917.52,10162.72
Exp/Cntr=0.3,0.1

Type RM Length L Ch R = 1 ,11181.12,121.082800,121.082800,121.082800
XS GIS Cut Line= 2
413062.732201487785703.784238741412978.530812621785939.027294308
#Sta/Elev= 28
9885.414100.75229897.32699.907759907.94897.73681 9929.1993.978579938.03292.82082
9939.81292.523219950.43389.460259961.05487.514969971.67586.955769982.29783.13154
9992.91877.70318 9997.3877.3013610003.5477.0619410014.1683.4366210024.7888.74812
10027.05 90.1623 10035.496.5346510046.02101.037410056.65101.522710067.27102.7112
 10086.4104.263510088.51104.376910099.13104.451710109.75105.655710116.08 106.557
10120.37107.285710130.99109.546210135.27 110.601
#Mann= 3 , 0 , 0
9885.414    0.12       09885.414    0.12       010135.27    0.12       0
#XS Ineff= 2 , 0
       0                               0
Bank Sta=9885.414,10135.27
Exp/Cntr=0.3,0.1

Type RM Length L Ch R = 1 ,11060.04,87.717100,87.717100,87.717100
XS GIS Cut Line= 2
412986.343312621785593.541183194412945.544701487785882.603683194
#Sta/Elev= 26
9878.41196.919089889.98495.441099900.08394.282829910.18293.42016 9930.3893.28698
9940.47993.034259950.57892.032329960.677 86.78969970.77782.736929980.87680.13056
9990.975 76.359210001.0773.4554510011.1774.4247810021.2778.5722410031.3784.43655
10041.4788.2650310071.7792.6481910081.8795.4973410091.9797.3343710102.0797.52628
10122.2699.1977610132.3699.9053910142.46100.380210152.56100.630410162.66101.0466
10170.34 102.704
#Mann= 3 , 0 , 0
9878.411    0.12       09878.411    0.12       010170.34    0.12       0
#XS Ineff= 2 , 0
       0                               0
Bank Sta=9878.411,10170.34
Exp/Cntr=0.3,0.1

Type RM Length L Ch R = 1 ,10972.32,110.428600,110.428600,110.428600
XS GIS Cut Line= 2
412916.030812621 785588.33284986412875.232201487 785877.39534986
#Sta/Elev= 28
9847.92194.132149855.29693.432889864.75392.867599874.85292.448169884.95191.51903
 9895.05  90.3249905.14989.630659925.34889.860359935.44789.695079955.645 89.9786
9965.74489.356279975.843 86.48659985.94279.454819996.04174.1957910006.1472.49666
10016.2477.0779110026.34 82.501710036.4488.5139910046.5491.1987510066.7495.00945
10076.8396.4466910086.9396.8010110097.0397.6546510107.1399.6852510117.23100.9891
10127.33103.767510137.43109.187510139.85110.0531
#Mann= 3 , 0 , 0
9847.921    0.12       09847.921    0.12       010139.85    0.12       0
#XS Ineff= 2 , 0
       0                               0
Bank Sta=9847.921,10139.85
Exp/Cntr=0.3,0.1

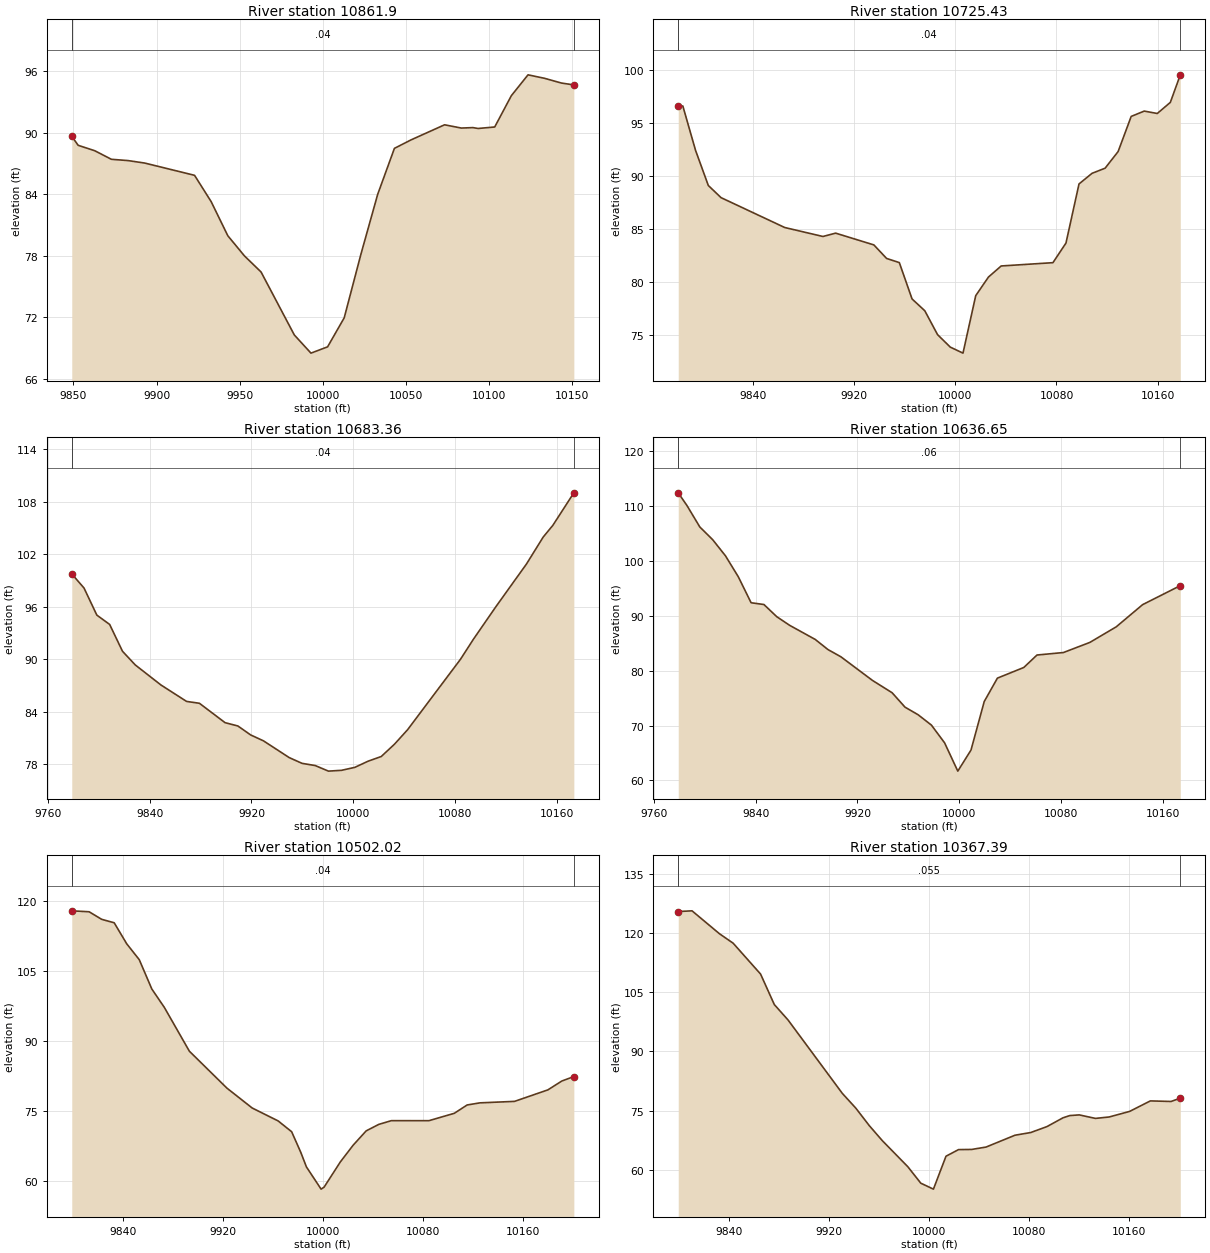
Type RM Length L Ch R = 1 , 10861.9,136.466700,136.466700,136.466700
XS GIS Cut Line= 6
412796.042282889785551.156505061 412793.66109898785701.130325271
412793.684626762785703.130186877412793.469264132785714.865182855
412785.182052057785789.528306699412780.391884532785852.471981982
#Sta/Elev= 29
9849.00789.661329852.85188.779499862.85388.247929872.85487.412639882.85587.28786
9892.85687.04691 9922.8685.849059932.86183.274899942.86379.948319952.86477.98172
9962.86576.408999982.86870.259629992.86968.4875110002.8769.0995510012.87 71.9355
10022.9378.15102   1003383.9909310043.0688.4803910053.1289.3123110073.2490.78173
 10083.390.4633910090.2690.5077810093.35 90.422410103.3890.56646 10113.493.62596
10123.4395.6610110133.46 95.317210143.4994.8594710150.98 94.6749
#Mann= 3 , 0 , 0
9849.007    0.04       09849.007    0.04       010150.98    0.04       0
#XS Ineff= 2 , 0
       0                               0
Bank Sta=9849.007,10150.98
Exp/Cntr=0.3,0.1

Type RM Length L Ch R = 1 ,10725.43,42.073600,42.073600,42.073600
XS GIS Cut Line= 3
412639.781391673785521.378974881412669.787415743785789.398884878
412700.600605142785912.651642452
#Sta/Elev= 30
9781.09996.590219784.74396.564689794.80592.382459804.86889.08079 9814.9387.93572
9865.24385.12255 9895.4384.277539905.49384.59212 9935.6883.484549945.74382.21069
9955.805 81.81729965.86878.39355 9975.93 77.28159985.99275.036619996.05573.85808
10006.1273.2903310016.18 78.703310026.2480.45733 10036.381.4999410077.1881.81028
10087.4983.65876 10097.889.2278710108.1190.2286810118.41 90.709710128.7292.28054
10139.0395.5874710149.3496.0897510159.6495.8631210169.9596.9081310177.8499.50507
#Mann= 3 , 0 , 0
9781.099    0.04       09781.099    0.04       010177.84    0.04       0
#XS Ineff= 2 , 0
       09973.953        10024.38       0
Bank Sta=9781.099,10177.84
Exp/Cntr=0.3,0.1

Type RM Length L Ch R = 1 ,10683.36,46.701000,46.701000,46.701000
XS GIS Cut Line= 3
412590.075310407785535.446733729412613.363804632785713.009995999
412671.499151485785920.887902921
#Sta/Elev= 30
9778.67199.727789788.30798.114469798.39295.020659808.47893.954379818.56390.89269
9828.64989.32353 9848.8287.038349868.99285.158649879.07784.947859899.24982.73309
9909.33482.35418 9919.4281.328329929.50680.652529949.67778.744749959.82278.08365
9970.20577.830839980.58977.195699990.97377.2899110001.3677.6280810011.7478.32867
10022.12 78.866710032.5180.2706710042.8981.9361210084.4389.9723210094.8192.30598
10112.3595.9929610136.34 100.85710149.48 103.93210157.11105.277410173.61108.9909
#Mann= 3 , 0 , 0
9778.671    0.04       09778.671    0.04       010173.61    0.04       0
#XS Ineff= 2 , 0
       09974.657        10019.52       0
Bank Sta=9778.671,10173.61
Exp/Cntr=0.3,0.1

Type RM Length L Ch R = 1 ,10636.65,134.632500,134.632500,134.632500
XS GIS Cut Line= 3
412545.124904646785548.168546679412568.224915743785724.294718221
412626.746508089 785933.55374539
#Sta/Elev= 30
 9779.01112.4315  9785.9110.10659795.985 106.2069806.071103.89649816.157100.9488
9826.24297.134999836.32892.386329846.41492.066369856.49989.849489866.58588.27994
9886.75685.700799896.84283.844229906.927 82.54069931.84578.21865 9947.2775.97432
9957.37773.35438 9967.7671.956549978.144 70.08229988.52866.844599998.911 61.6871
 10009.365.5313310019.6874.3675710030.0678.6416710050.8380.5881210061.2182.85762
10081.9883.3104910102.7585.1514710123.5287.9967810144.2892.0412110173.9395.50896
#Mann= 3 , 0 , 0
 9779.01    0.06       0 9779.01    0.06       010173.93    0.06       0
#XS Ineff= 2 , 0
       09973.065        10020.04       0
Bank Sta=9779.01,10173.93
Exp/Cntr=0.3,0.1

Type RM Length L Ch R = 1 ,10502.02,134.632500,134.632500,134.632500
XS GIS Cut Line= 6
412476.163154119785551.162821166412479.313644014785690.262523538
412441.302149302785762.380138743412436.574187495 785800.36288399
412446.756781399785866.254784988 412476.53216815 785933.68069658
#Sta/Elev= 30
9799.119117.8534    9813 117.6519823.031116.03179833.063115.28929843.095110.7798
9853.126107.37699863.158101.0981 9873.1997.141339893.21587.749289923.27579.82997
9943.49675.566889964.23872.800029975.04170.485089982.37866.046879986.84562.94795
9998.59258.17495   1000158.6013310014.1164.0507610024.4367.6535610034.69 70.6685
10044.7772.0611810054.7972.8542710084.8872.8527410105.1774.4341510115.4676.22066
10125.7476.6747110153.3876.9921610180.0779.4606110191.1881.3536210200.8282.31632
#Mann= 3 , 0 , 0
9799.119    0.04       09799.119    0.04       010200.82    0.04       0
#XS Ineff= 2 , 0
       0                               0
Bank Sta=9799.119,10200.82
Exp/Cntr=0.3,0.1

Type RM Length L Ch R = 1 ,10367.39,134.632500,134.632500,134.632500
XS GIS Cut Line= 6
412263.061280207785564.931609172412324.330819769785705.155889097
412337.790239141785777.735050391 412342.88174136785792.193212257
 412359.79634541785818.430700945412439.455884671785918.839819695
#Sta/Elev= 30
9799.043125.50389810.091125.68589832.038119.87229843.011117.46749864.958109.6327
9875.932101.90389886.90597.997649930.35279.370049941.13975.626549951.926  71.186
9962.30867.390339982.81560.741879993.17656.5727710003.2955.0648110013.3463.41395
10023.3865.0935610033.8365.1338510045.3765.7368310068.59  68.74710081.1769.42563
10094.1170.9270310107.0573.1693810112.3973.7262910119.9973.9016610132.9373.01132
10143.9173.3717310160.2874.7830710176.8877.4503110193.4777.3082210200.8778.14813
#Mann= 3 , 0 , 0
9799.043   0.055       09799.043   0.055       010200.87   0.055       0
#XS Ineff= 2 , 0
       0                               0
Bank Sta=9799.043,10200.87
Exp/Cntr=0.3,0.1

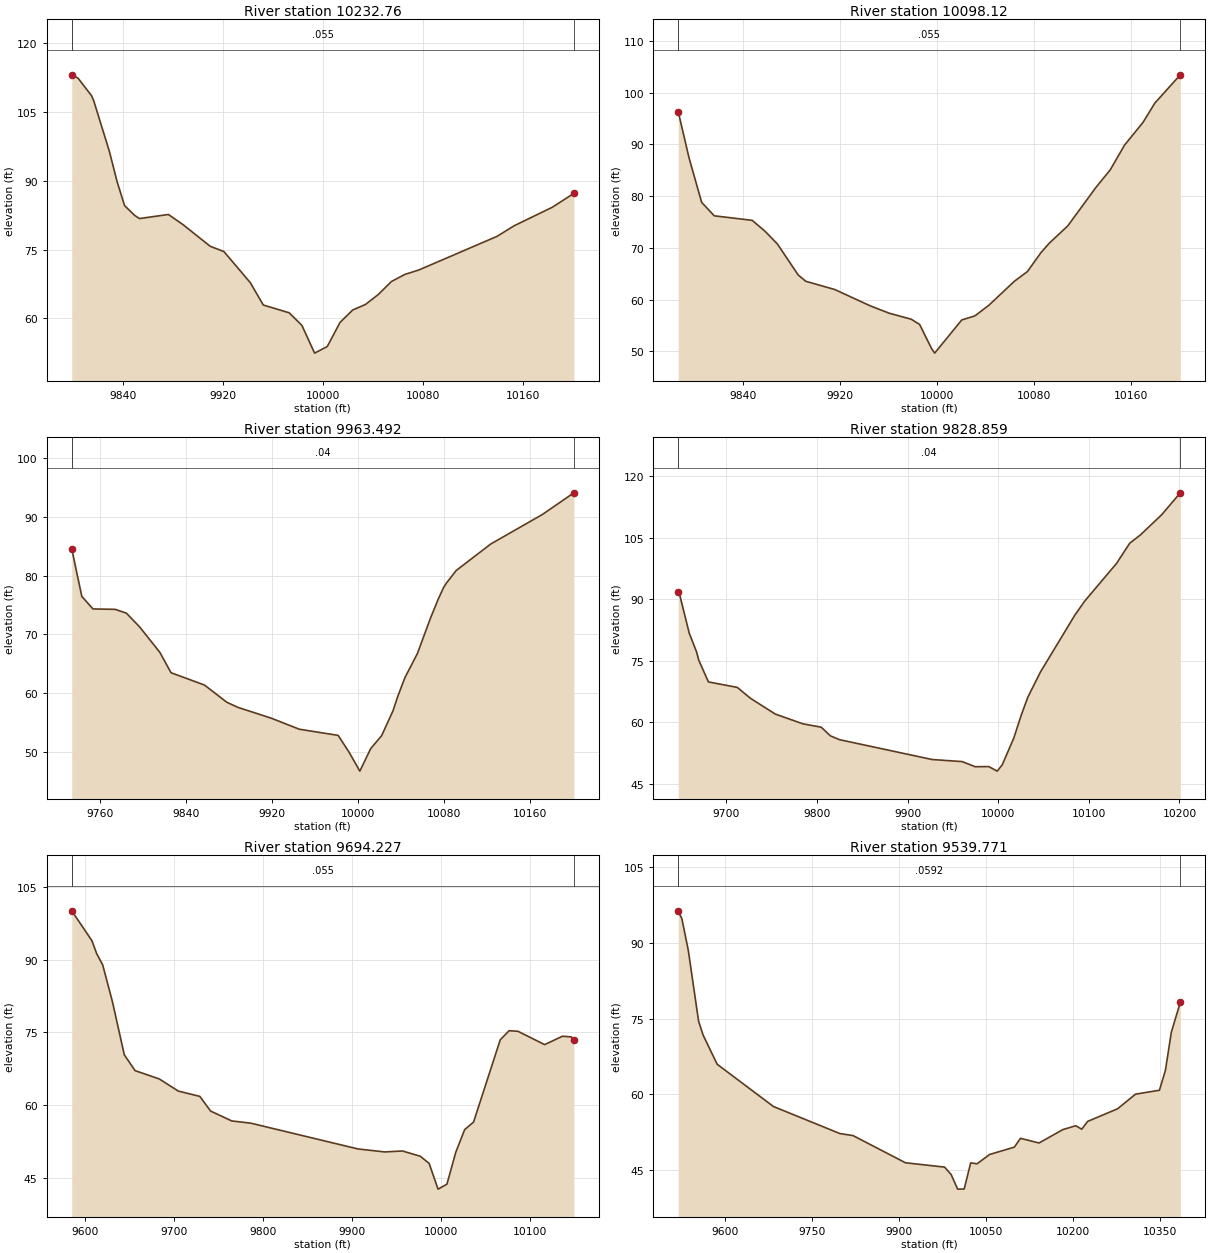
Type RM Length L Ch R = 1 ,10232.76,134.632400,134.632400,134.632400
XS GIS Cut Line= 6
 412110.98765866785785.499653098412160.999358681785820.904782853
412216.684860363785848.755250422412367.869344655785889.484753144
412406.868078382785917.662205867412456.473771334785970.863626033
#Sta/Elev= 30
 9799.08113.09919804.099112.37079814.891108.55729816.609  107.48 9829.1296.47636
9835.30689.858199841.32984.59215 9849.5382.429789853.24381.765259876.39982.65769
9887.833 80.50429909.89975.720579920.86174.572679941.91267.812819952.39762.91349
9973.12161.220629983.277 58.47689993.43452.4321110003.5853.8734610013.7659.11688
10023.9361.83344 10034.163.0340710044.3865.2050510054.9168.04078 10065.769.59513
10076.7570.5437510139.4477.8873110153.37 80.230810183.5384.2111810200.91 87.2503
#Mann= 3 , 0 , 0
 9799.08   0.055       0 9799.08   0.055       010200.91   0.055       0
#XS Ineff= 2 , 0
       0                               0
Bank Sta=9799.08,10200.91
Exp/Cntr=0.3,0.1

Type RM Length L Ch R = 1 ,10098.12,134.632500,134.632500,134.632500
XS GIS Cut Line= 6
412123.453835189785816.461435094412147.325362951785897.841643408
412176.622237951785943.414560094412235.581786394785986.963978648
412337.487902045786032.959833771412411.605858207786083.863170281
#Sta/Elev= 30
9786.71496.296399795.61287.393669806.03478.781929816.45576.186689847.71975.30823
9858.141 73.24819868.56270.734889885.71664.746729891.921 63.53919915.69761.96139
9945.20158.78728 9960.98 57.35359978.863 56.21879985.84555.206239995.69450.56033
9998.27749.6608310020.6256.0703510031.4656.8536410042.9358.9010410063.9663.52401
 10074.865.4209510085.85 69.037710092.7770.8855210108.1174.2458210131.4181.70051
10143.1485.0654710154.8789.8246210170.2194.24391 10179.9  97.95710200.93103.4183
#Mann= 3 , 0 , 0
9786.714   0.055       09786.714   0.055       010200.93   0.055       0
#XS Ineff= 2 , 0
       0                               0
Bank Sta=9786.714,10200.93
Exp/Cntr=0.3,0.1

Type RM Length L Ch R = 1 ,9963.492,134.632500,134.632500,134.632500
XS GIS Cut Line= 6
 412118.02848798 785835.99268508412183.333101898786069.769301936
412189.208941579786112.952394366412193.849913895786126.658909827
 412219.30660221786167.240790561412293.152857274786260.108408347
#Sta/Elev= 30
9733.47584.549289742.82776.47609 9753.2174.343549773.97674.269989784.35973.61981
9796.55671.306149815.50766.95356 9825.8963.491139857.03961.398439877.80458.47083
9888.18757.596959919.33655.754189945.22953.886089981.489  52.8349991.59649.99057
10001.6846.7559510011.7750.5836710021.9652.7862810032.5257.0102210036.8159.37457
10043.6262.65338 10055.366.7751810067.4272.7663410074.6575.9982110079.5477.95442
10082.2678.7345210091.4180.8832310123.5485.3843410171.74 90.418410200.9194.09089
#Mann= 3 , 0 , 0
9733.475    0.04       09733.475    0.04       010200.91    0.04       0
#XS Ineff= 2 , 0
       0                               0
Bank Sta=9733.475,10200.91
Exp/Cntr=0.3,0.1

Type RM Length L Ch R = 1 ,9828.859,134.632500,134.632500,134.632500
XS GIS Cut Line= 6
412101.752446294785843.588171184412069.615449786785934.011195198
412048.584043533786063.857268423412055.094460189786105.089907303
412074.633747429786147.061330602 412221.97706908786332.521685019
#Sta/Elev= 30
9647.07891.837499648.57691.216139659.18981.753339667.24177.206179669.80275.10969
9680.414 69.84079712.25368.501199726.96365.813619754.174 61.99489784.56559.61403
9804.82558.791659814.956  56.6719825.08655.742379927.19750.901119960.30750.39571
9974.59849.144619989.67149.18182    999948.0693510004.5449.6211210017.2256.11814
10025.7261.89585 10032.866.13753 10046.772.2767510084.6186.1404310095.6189.60695
10130.6898.7854510145.07103.679710156.83105.702610180.35 110.63710200.95115.9951
#Mann= 3 , 0 , 0
9647.078    0.04       09647.078    0.04       010200.95    0.04       0
#XS Ineff= 2 , 0
       09934.485                       0
Bank Sta=9647.078,10200.95
Exp/Cntr=0.3,0.1

Type RM Length L Ch R = 1 ,9694.227,154.455800,154.455800,154.455800
XS GIS Cut Line= 6
412100.946345419 785826.30851385412002.205025971785969.537680551
  411994.5837138785983.527486488411978.525080264786120.025871441
411981.997302473786291.900871441411981.997302473 786357.87309368
#Sta/Elev= 30
9584.644100.06859607.34793.902079612.73991.220929619.49388.894879630.35781.37189
9643.785 70.35679655.93167.098419683.213 65.37739704.51562.886479728.80761.78313
9740.95358.755519764.83156.715229786.09356.264599906.92150.936079936.96150.32281
9956.96550.520789976.96949.434879986.97147.953279996.973   42.6510006.9843.67498
10016.9850.2785910026.9854.9353210036.9856.4900110066.9973.4517410076.9975.33625
10086.9975.2117710116.9972.4619610136.9974.1916710146.9974.0552410149.8673.35256
#Mann= 3 , 0 , 0
9584.644   0.055       09584.644   0.055       010149.86   0.055       0
#XS Ineff= 2 , 0
       09971.272                       0
Bank Sta=9584.644,10149.86
Exp/Cntr=0.3,0.1

Type RM Length L Ch R = 1 ,9539.771,57.726300,57.726300,57.726300
XS GIS Cut Line= 6
412074.904678762785829.780736074411976.163359314 785973.00990276
411896.953289866786118.409208313411816.658150971786274.659208313
411764.574817657786414.633166656411715.746692657786609.945666641
#Sta/Elev= 30
9519.41996.382429525.75894.798819536.86988.476989554.48874.525839562.19671.78184
9586.48865.968469683.65757.579219798.14152.221629820.91651.814149911.34446.42506
9978.80345.568069990.04644.0948510001.2941.1999510012.5341.2184510023.7846.40381
   1003546.2294310056.3448.0698210099.0249.5186210109.6951.27464 10141.750.34732
10182.7753.0079810204.9853.7641610215.2953.0827510225.5954.6332410277.1357.12971
10308.0660.0292510349.2960.80711 10359.664.73336 10369.972.3429310385.31 78.2452
#Mann= 3 , 0 , 0
9519.419  0.0592       09519.419  0.0592       010385.31  0.0592       0
#XS Ineff= 2 , 0
       09945.387        10023.07       0
Bank Sta=9519.419,10385.31
Exp/Cntr=0.3,0.1

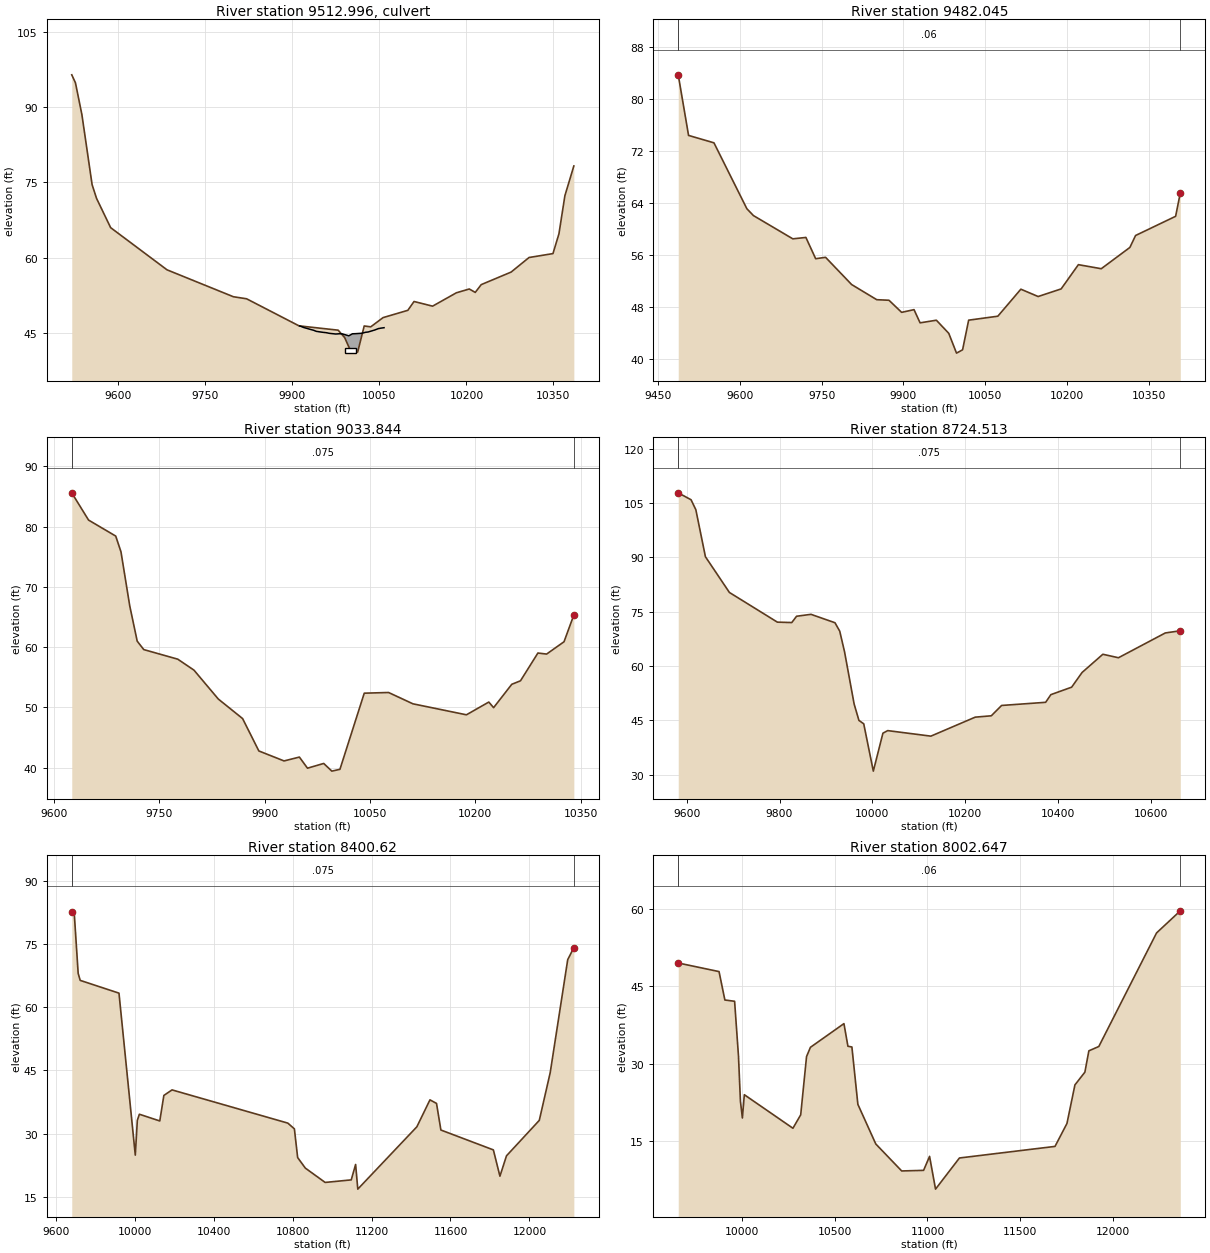
Type RM Length L Ch R = 2 ,9512.996,,,
Bridge Culvert--1,0,-1,-1, 0
Deck Dist Width WeirC Skew NumUp NumDn MinLoCord MaxHiCord MaxSubmerge Is_Ogee
17.863,22,2.6,0,22,22, , , 0.95, 0, 0,0,,
 9912.43 9914.08 9918.91 9930.09 9936.44 9941.27 9952.45 9958.80 9963.63 9974.81
 9981.16 9985.99 9997.1710003.5210008.3510019.5310025.8810030.7110041.8910048.25
10053.0710058.01
   46.40   46.35   46.12   45.75   45.55   45.33   45.14   45.06   44.94   44.80
   44.86   44.83   44.45   44.85   44.87   44.95   45.14   45.21   45.60   45.88
   45.98   46.06
                                                                                
                                                                                
                
 9912.43 9914.08 9918.91 9930.09 9936.44 9941.27 9952.45 9958.80 9963.63 9974.81
 9981.16 9985.99 9997.1710003.5210008.3510019.5310025.8810030.7110041.8910048.25
10053.0710058.01
   46.40   46.35   46.12   45.75   45.55   45.33   45.14   45.06   44.94   44.80
   44.86   44.83   44.45   44.85   44.87   44.95   45.14   45.21   45.60   45.88
   45.98   46.06
                                                                                
                                                                                
                
BR Coef=-1 , 0 , 0 ,, 0 ,,,0.8,-1,,0,
WSPro=,,,, 1 ,,,, 0 ,,,, 0 ,,,,-1 ,-1 ,-1 , 0 , 0 , 0 , 0 , 0
Culvert=2,1,18,22,0.013,0.5,1,8,3,41,10000,41,10000,Culvert #1, 0, 17.863
Culvert Bottom n=0.013
BC Design=,, 0 ,, 0 ,,,,,,

Type RM Length L Ch R = 1 ,9482.045,448.200400,448.200400,448.200400
XS GIS Cut Line= 6
412045.607803732785790.718236074411863.316137105786063.070666656
411814.488012075786152.046361074411762.404678732786258.383166656
411703.810928732786431.994277745 411646.30224818786613.200874969
#Sta/Elev= 30
9486.87383.765639505.81374.423199552.39573.28108 9612.7563.120869624.82162.06183
9697.07258.476219721.04158.690879738.97755.411599757.12155.627889804.93451.42889
9851.02749.092039873.46349.005839896.65547.141549919.38847.558579930.52345.52474
9960.40445.929699983.13843.903559997.334 40.854210008.4741.36764 10019.645.93493
10073.1546.5476710115.3750.7118810147.0349.5822510189.2550.7546310220.8954.49352
10262.8653.8697310315.3257.1470910325.8158.9912110399.2561.9510610407.8565.56147
#Mann= 3 , 0 , 0
9486.873    0.06       09486.873    0.06       010407.85    0.06       0
#XS Ineff= 2 , 0
       09926.808        10025.86       0
Bank Sta=9486.873,10407.85
Exp/Cntr=0.3,0.1

Type RM Length L Ch R = 1 ,9033.844,309.331200,309.331200,309.331200
XS GIS Cut Line= 3
411263.665625989786114.296093926 411560.97465378786628.619010553
411632.589237094786726.275260568
#Sta/Elev= 30
9625.265 85.62489649.17981.101559687.87678.444469695.38175.819239707.85866.85261
9718.48260.997289727.83959.596729776.235 58.00659799.33656.184879833.98851.38843
 9868.6448.140069891.74142.768669927.65541.109779949.49341.751179961.04439.90696
9984.14540.692789995.69639.4180610007.2539.71742 10041.952.3598510076.5552.47208
 10111.250.5939110187.4248.7691210219.3450.8876810226.1449.9551610252.0553.83627
10264.4554.4139410289.2559.0257210301.6558.8522110326.4560.8985410340.4465.34512
#Mann= 3 , 0 , 0
9625.265   0.075       09625.265   0.075       010340.44   0.075       0
#XS Ineff= 2 , 0
       09947.462        10070.81       0
Bank Sta=9625.265,10340.44
Exp/Cntr=0.3,0.1

Type RM Length L Ch R = 1 ,8724.513,323.892800,323.892800,323.892800
XS GIS Cut Line= 3
411082.945766687786188.299254611411252.216600031786835.000643507
411438.848544478787203.924254611
#Sta/Elev= 30
9581.706107.78069609.306105.86929619.643103.12269640.31790.132479692.00180.26947
 9795.3772.074689826.38171.961629836.717 73.70519867.72874.233239919.41271.91638
9929.74969.579349940.08663.89646 9960.76 49.46739971.09744.942949981.43444.00965
10002.1130.9429410022.78 41.420910033.1242.1281210126.1540.6018910221.6945.84459
10256.3646.2196510278.5149.0726110373.47 49.941610384.6752.05747 10429.554.12102
10451.9158.1732910496.7463.2063210530.3662.2470510631.2269.0861110663.6469.69867
#Mann= 3 , 0 , 0
9581.706   0.075       09581.706   0.075       010663.64   0.075       0
#XS Ineff= 2 , 0
       0                10048.34       0
Bank Sta=9581.706,10663.64
Exp/Cntr=0.3,0.1

Type RM Length L Ch R = 1 , 8400.62,397.973000,397.973000,397.973000
XS GIS Cut Line= 3
410800.827711135786383.611754611410970.098544478787030.313143507
411777.390211135 788723.02147682
#Sta/Elev= 30
9681.13582.665779692.90683.00556 9713.5868.118379723.91766.448619920.31863.41091
10003.0124.8527910013.3533.1417310023.6934.5866710127.0632.9858910147.7339.05753
10189.0840.3802110775.8232.4729710809.0631.1038510825.6124.2737210864.4521.76648
   1096518.3502311097.1118.9575311119.2722.6311811130.3516.75896 11429.631.59549
11495.9638.0085911529.1937.1623711551.3530.8295411817.25 26.098211850.4919.83995
11883.7224.6870912049.9133.1255612105.3144.5058612193.9471.3806512224.9874.23589
#Mann= 3 , 0 , 0
9681.135   0.075       09681.135   0.075       012224.98   0.075       0
#XS Ineff= 2 , 0
       0                   10036       0
Bank Sta=9681.135,12224.98
Exp/Cntr=0.3,0.1

Type RM Length L Ch R = 1 ,8002.647,412.958700,412.958700,412.958700
XS GIS Cut Line= 3
410405.862433374786505.139532387410644.577711135787260.347865731
411343.362433404789044.202032387
#Sta/Elev= 30
9655.88549.54351 9875.9847.877239907.443 42.36559959.88142.118459980.85631.47023
9991.344 22.743210001.8319.4868710012.3223.9975810274.5117.4946710316.4620.10547
10347.9331.39518 10368.9 33.191410549.5837.7866110571.0633.3986710592.5433.25084
10624.7622.1306410721.4214.4428410861.039.21193710979.179.32703111011.3912.03904
11043.61 5.6880811172.4911.7255411688.0113.9735311752.4418.42582 11795.4 25.9012
 11849.128.3705811870.5832.5078111924.28 33.350812235.7455.3791212363.7659.66157
#Mann= 3 , 0 , 0
9655.885    0.06       09655.885    0.06       012363.76    0.06       0
#XS Ineff= 2 , 0
       0                10028.04       0
Bank Sta=9655.885,12363.76
Exp/Cntr=0.3,0.1