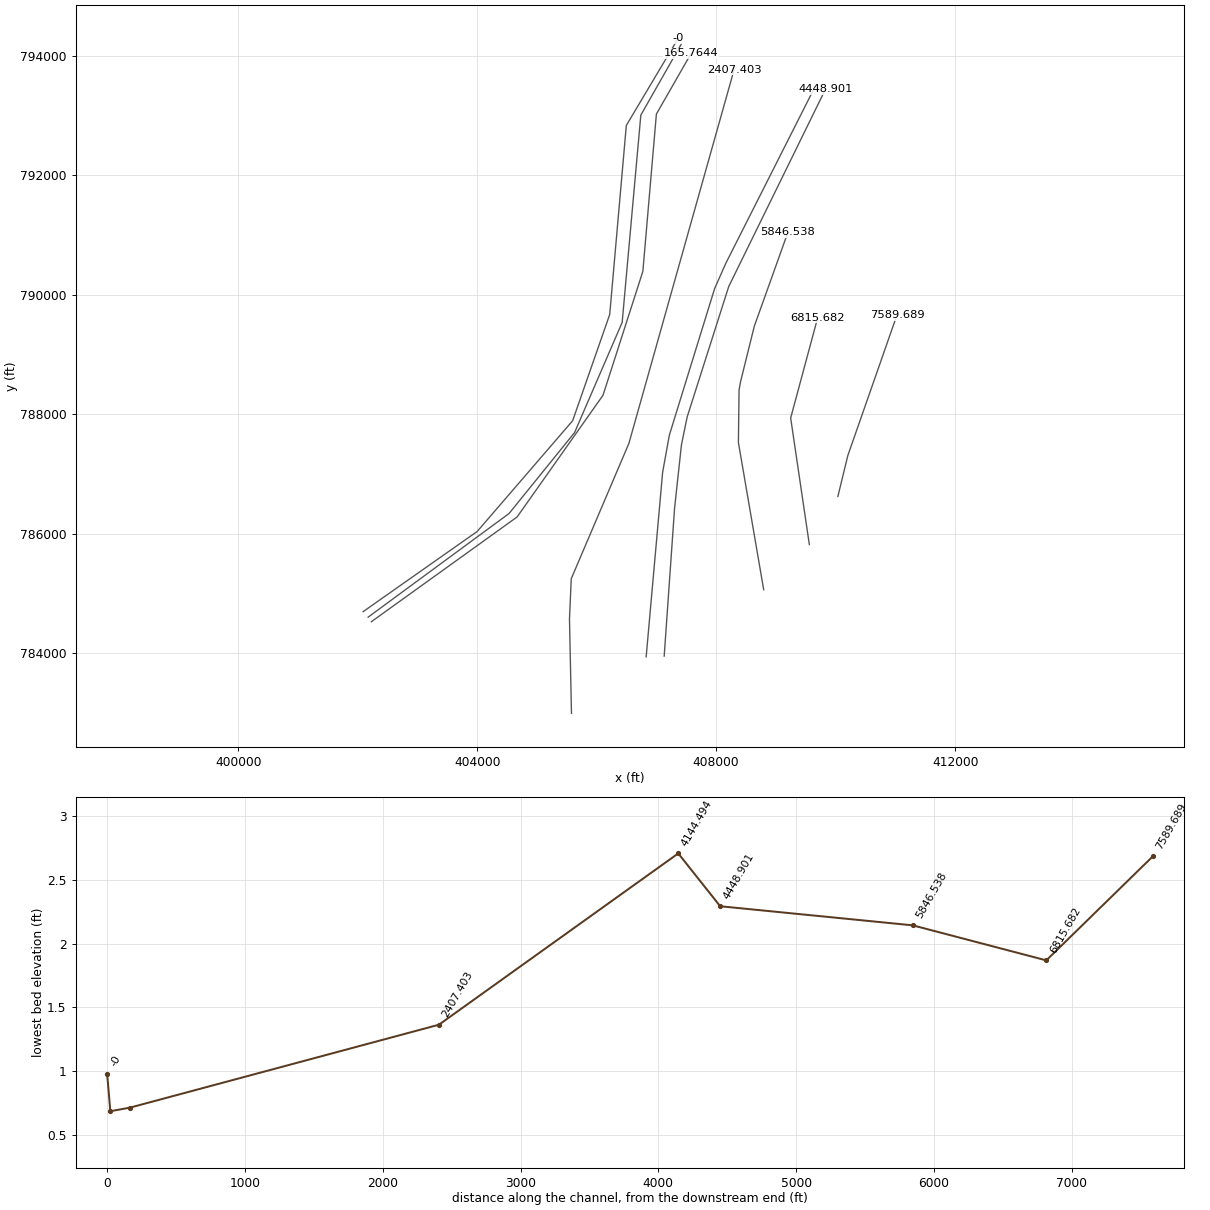
HEC-RAS study 3716_ras.prj: 3716

--- 3716_ras.g01 (geometry) --- (continued)

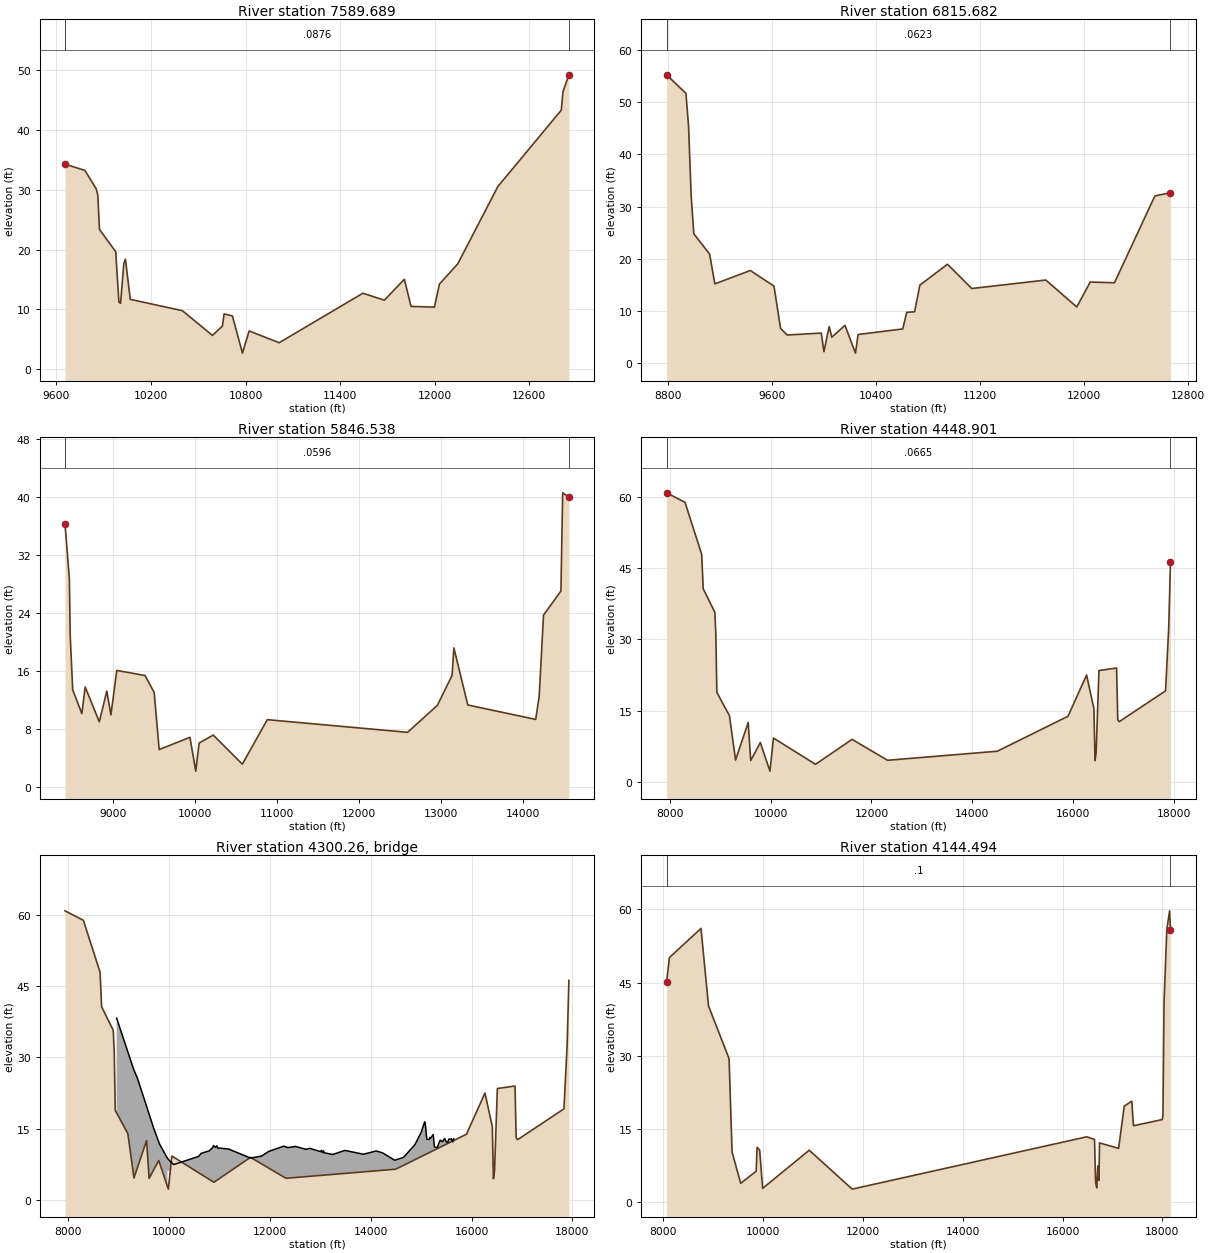
Type RM Length L Ch R = 1 ,7589.689,774.006100,774.006100,774.006100
XS GIS Cut Line= 3
410036.938822269786622.327032387410203.605488926787307.222865731
411026.522155583 789660.52147682
#Sta/Elev= 30
9654.11934.249959780.372 33.22469852.41430.139789862.70629.055499872.99823.35909
9975.91619.64445  9996.511.2196410006.7910.9963410027.3817.6615210037.6718.38864
10068.5411.6698110399.029.78051410589.715.64823110653.277.21187110663.879.242544
10716.848.895891 10780.42.68465910822.776.38659811013.464.42138811544.7312.69345
11680.8711.5315711807.9915.0218811850.3710.4929811998.6810.3693712030.4614.22032
12146.9917.6083412401.2530.5229212803.8143.28579 12814.446.3494812852.0349.18902
#Mann= 3 , 0 , 0
9654.119  0.0876       09654.119  0.0876       012852.03  0.0876       0
#XS Ineff= 2 , 0
       0                10042.97       0
Bank Sta=9654.119,12852.03
Exp/Cntr=0.3,0.1

Type RM Length L Ch R = 1 ,6815.682,969.144900,969.144900,969.144900
XS GIS Cut Line= 3
409559.508266717785817.639532387409247.008266717787935.695087925
409698.397155583789611.042310163
#Sta/Elev= 30
8787.066  55.2878936.02151.730068956.23845.403418976.45431.949818996.67124.76446
 9117.9720.898299158.40315.159529431.32617.730269613.27414.729289663.8166.612251
9714.3575.3458589977.1725.7183799997.3882.14594410037.826.97434910058.044.923512
10159.127.20691610239.991.868195 10260.25.44386910603.886.51174210634.219.699615
10694.869.79658510735.2914.9215110948.0418.9268611134.4614.2697311704.0815.89848
11942.2810.7294712045.8415.5177612232.2615.3742912542.9632.0354912663.1432.66482
#Mann= 3 , 0 , 0
8787.066  0.0623       08787.066  0.0623       012663.14  0.0623       0
#XS Ineff= 2 , 0
       09835.783        10205.12       0
Bank Sta=8787.066,12663.14
Exp/Cntr=0.3,0.1

Type RM Length L Ch R = 1 ,5846.538,1397.636100,1397.636100,1397.636100
XS GIS Cut Line= 6
408795.436479717785062.271615252408372.259396493787525.379254133
408383.110090852788404.285504133408409.151757598788547.514670983
408637.797615469789470.479659408409201.500868486791046.349345365
#Sta/Elev= 30
8417.29536.274548470.79628.684318480.94320.940138511.38213.372318622.99410.08254
 8663.5813.754258836.0718.9446488927.38913.185698978.122 9.904889049.14816.03831
9394.12915.335469505.741 12.9983 9566.625.1182579942.041 6.8071310013.072.142794
10053.656.01446210226.147.11933110581.273.10465210885.679.24511812597.327.497412
12960.4411.2149113140.9915.3573213162.2319.1467113332.1611.2707114160.569.276672
14203.0412.4493414256.1523.6682914468.5626.99715 14489.840.5465914565.5839.93564
#Mann= 3 , 0 , 0
8417.295  0.0596       08417.295  0.0596       014565.58  0.0596       0
#XS Ineff= 2 , 0
       09725.476        10686.86       0
Bank Sta=8417.295,14565.58
Exp/Cntr=0.3,0.1

Type RM Length L Ch R = 1 ,4448.901,304.407200,304.407200,304.407200
XS GIS Cut Line= 6
407130.146212131783950.792114064407303.757323146786424.750447392
 407418.77468425787485.948364049407514.260795385787952.528225169
408210.441350996790136.990030706409828.277914912  793436.4035597
#Sta/Elev= 30
7938.55860.822888303.662 58.83158634.47447.901168664.54740.655198895.11335.70644
8915.16231.125138935.21118.849629185.82613.937959306.1214.6220229556.73612.51921
9606.8594.5344449797.3268.3050789987.7942.29238310057.979.245406 10891.63.728689
11616.828.97314312320.234.57273914495.786.47872215898.25  13.83216266.3622.50248
16411.3715.4339816433.684.48416216455.996.23518216511.7623.4551716861.83 23.9768
 16884.413.1191316913.3312.69273 17832.3 19.175817894.9532.4948117929.9846.20189
#Mann= 3 , 0 , 0
7938.558  0.0665       07938.558  0.0665       017929.98  0.0665       0
#XS Ineff= 2 , 0
       0 9935.48        10070.51       0
Bank Sta=7938.558,17929.98
Exp/Cntr=0.3,0.1

Type RM Length L Ch R = 3 , 4300.26,,,
BEGIN DESCRIPTION:
END DESCRIPTION:
Bridge Culvert--1,0,-1,-1, 0
Deck Dist Width WeirC Skew NumUp NumDn MinLoCord MaxHiCord MaxSubmerge Is_Ogee
95.445200,113.516800,2.6,0, 60, 60, , , 0.95, 0, 0,0,,
 8962.59 9303.92 9374.11 9705.05 9815.36 9970.47 9970.4710029.5310029.5310096.15
10587.7710638.2810799.9310870.6510880.7510921.1710951.4810961.5811183.8411616.31
11830.4411981.9812275.6612360.0412507.7212718.6812792.5213014.0313024.5813045.67
13064.9913077.3213246.0913488.7013856.6514108.4614234.3714475.7014650.8714877.64
15000.4815070.3915081.7315106.5615115.7415161.1015172.4315183.7715240.4715263.14
15319.8315376.5315421.8815467.2315501.2515530.9015546.6015603.2915625.9715646.40
   38.25   27.36   25.64   14.87   11.73    8.77    8.77    8.08    8.08    7.46
    9.17    9.81   10.35   11.07   11.47   11.11   11.41   10.97   10.72    8.83
    9.22   10.24   11.33   11.02   11.27   10.66   10.87   10.16   10.46   10.01
   10.34    9.94    9.58   10.43    9.63   10.32    9.93    8.37    8.97   11.66
   14.23   16.44   16.20   13.38   12.74   12.76   13.16   12.96   13.78   11.16
   11.04   12.58   12.27   12.93   12.20   12.15   12.76   12.87   12.23   12.88
 -961.75 -972.64 -974.36 -985.13 -988.27 -991.23    6.27    5.58 -991.92 -992.54
 -990.83 -990.19 -989.65 -988.93 -988.53 -988.89 -988.59 -989.03 -989.28 -991.17
 -990.78 -989.76 -988.67 -988.98 -988.73 -989.34 -989.13 -989.84 -989.54 -989.99
 -989.66 -990.06 -990.42 -989.57 -990.37 -989.68 -990.07 -991.63 -991.03 -988.34
 -985.77 -983.56 -983.80 -986.62 -987.26 -987.24 -986.84 -987.04 -986.22 -988.84
 -988.96 -987.42 -987.73 -987.07 -987.80 -987.85 -987.24 -987.13 -987.77 -987.12
 8962.59 9303.92 9374.11 9705.05 9815.36 9970.47 9970.4710029.5310029.5310096.15
10587.7710638.2810799.9310870.6510880.7510921.1710951.4810961.5811183.8411616.31
11830.4411981.9812275.6612360.0412507.7212718.6812792.5213014.0313024.5813045.67
13064.9913077.3213246.0913488.7013856.6514108.4614234.3714475.7014650.8714877.64
15000.4815070.3915081.7315106.5615115.7415161.1015172.4315183.7715240.4715263.14
15319.8315376.5315421.8815467.2315501.2515530.9015546.6015603.2915625.9715646.40
   38.25   27.36   25.64   14.87   11.73    8.77    8.77    8.08    8.08    7.46
    9.17    9.81   10.35   11.07   11.47   11.11   11.41   10.97   10.72    8.83
    9.22   10.24   11.33   11.02   11.27   10.66   10.87   10.16   10.46   10.01
   10.34    9.94    9.58   10.43    9.63   10.32    9.93    8.37    8.97   11.66
   14.23   16.44   16.20   13.38   12.74   12.76   13.16   12.96   13.78   11.16
   11.04   12.58   12.27   12.93   12.20   12.15   12.76   12.87   12.23   12.88
 -961.75 -972.64 -974.36 -985.13 -988.27 -991.23    6.27    5.58 -991.92 -992.54
 -990.83 -990.19 -989.65 -988.93 -988.53 -988.89 -988.59 -989.03 -989.28 -991.17
 -990.78 -989.76 -988.67 -988.98 -988.73 -989.34 -989.13 -989.84 -989.54 -989.99
 -989.66 -990.06 -990.42 -989.57 -990.37 -989.68 -990.07 -991.63 -991.03 -988.34
 -985.77 -983.56 -983.80 -986.62 -987.26 -987.24 -986.84 -987.04 -986.22 -988.84
 -988.96 -987.42 -987.73 -987.07 -987.80 -987.85 -987.24 -987.13 -987.77 -987.12
Pier Skew, UpSta & Num, DnSta & Num=  ,10000.00, 2 ,10000.00, 2 , 0 , 0 , 0 ,,
    3.00    3.00
 -991.57    8.43
    3.00    3.00
 -991.57    8.43
BR Coef=-1 , 0 , 0 ,, 0 ,,,0.8,0,1,0,
WSPro=,,,, 1 ,,,, 0 ,,,, 0 ,,,,-1 ,-1 ,-1 , 0 , 0 , 0 , 0 , 0
BC Design=,, 0 ,, 0 ,,,,,,

Type RM Length L Ch R = 1 ,4144.494,1737.091100,1737.091100,1737.091100
XS GIS Cut Line= 6
406828.207554638783938.205308482407104.104545385787028.049058497
407216.951767594787650.878919616407974.330239832790102.267808497
408161.830239832790525.878919601409664.492276847793500.618502945
#Sta/Elev= 30
8065.798 45.12888122.83550.119868755.52556.083738906.16640.208629317.916 29.4235
9378.17210.318639550.808 3.887469860.2226.3627359880.30711.266339930.52110.71054
9990.7772.86762510924.1610.6723211784.812.70654816484.6213.41625 16640.712.87315
16662.994.06609316685.292.98368716707.597.46180116729.884.49694616741.03 12.1678
17123.61 11.054717236.7219.6931117387.63 20.720617421.0715.6824118000.7816.95141
18011.9317.7505318034.2340.9241618089.9755.9042618145.7159.6830818163.1255.83797
#Mann= 3 , 0 , 0
8065.798     0.1       08065.798     0.1       018163.12     0.1       0
#XS Ineff= 2 , 0
       09929.138        10083.34       0
Bank Sta=8065.798,18163.12
Exp/Cntr=0.3,0.1

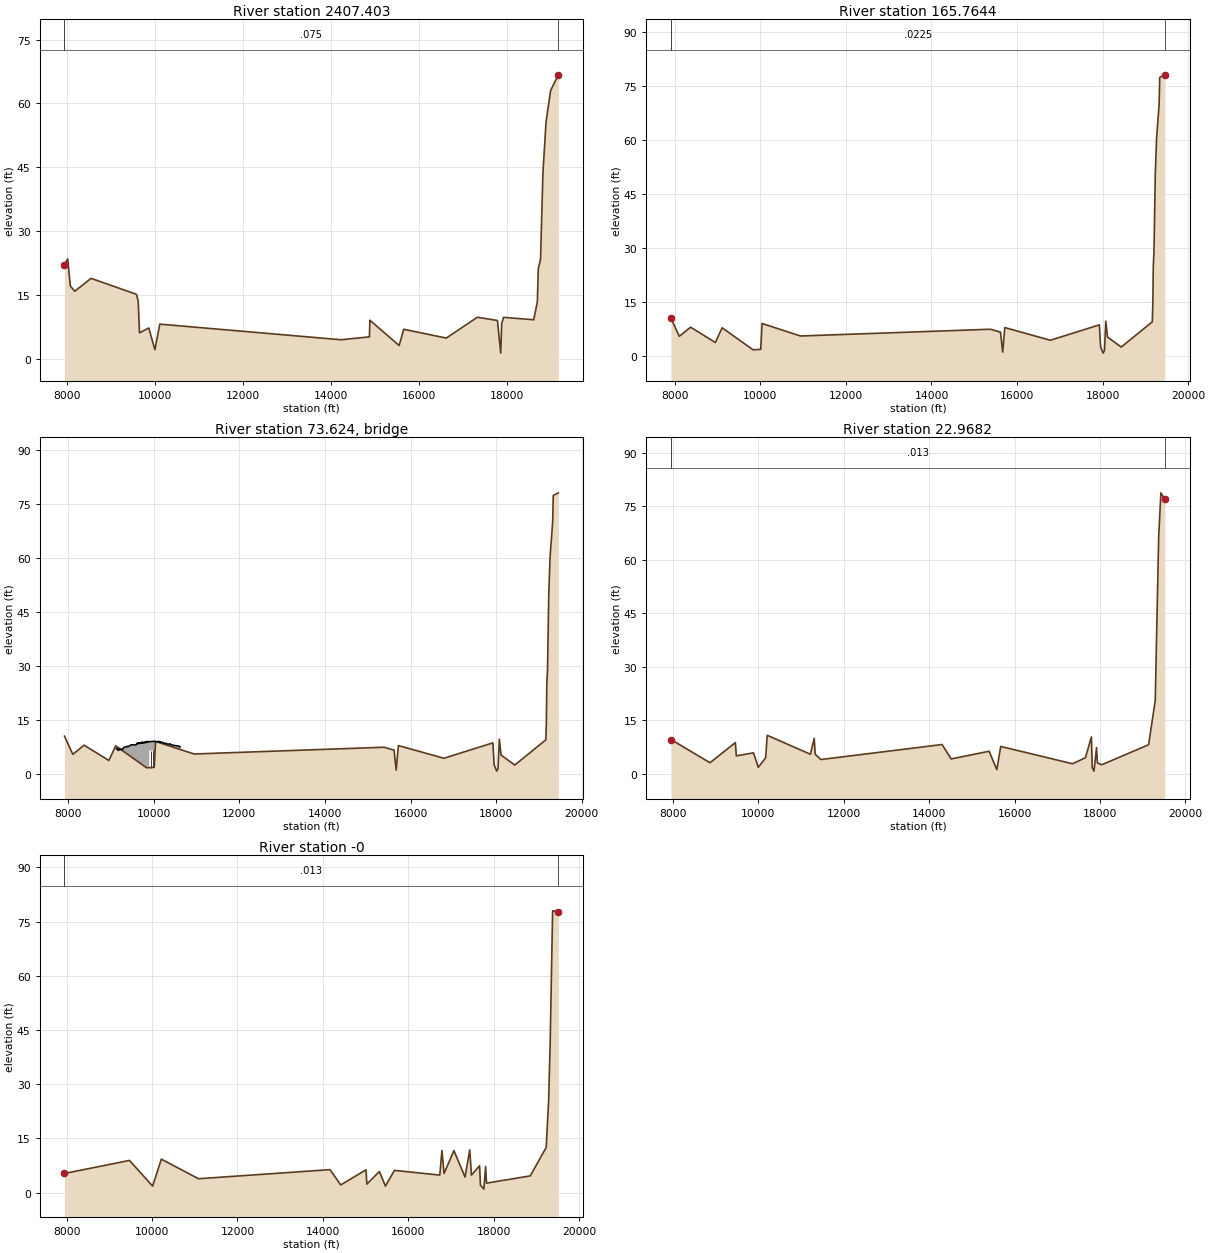
Type RM Length L Ch R = 1 ,2407.403,2241.638700,2241.638700,2241.638700
XS GIS Cut Line= 5
405578.364720464782992.103791162405544.799905658784570.807494864
405574.313794553785245.286661536406539.492276907787511.035169616
408300.008239001793764.383883774
#Sta/Elev= 30
7948.10622.083368021.01923.499088081.03217.130968181.05515.888188551.13918.92354
9581.41115.179129621.44913.664319651.4786.1375089861.6797.26402510001.812.182295
10111.928.17374714227.484.50488414871.585.18460814881.979.09157215546.853.155868
15650.746.95984216616.894.90059717323.339.79213517777.689.02737817853.151.363858
17873.938.25770917915.499.76433118601.149.20134718684.2513.3981418705.0321.10266
18756.9723.4380218810.9143.6944318881.6455.6176418985.5363.04481 19161.566.71931
#Mann= 3 , 0 , 0
7948.106   0.075       07948.106   0.075       0 19161.5   0.075       0
#XS Ineff= 2 , 0
       09871.192        10089.34       0
Bank Sta=7948.106,19161.5
Exp/Cntr=0.3,0.1

Type RM Length L Ch R = 1 ,165.7644,142.796200,142.796200,142.796200
XS GIS Cut Line= 6
402228.863852412784526.297946274 404669.06403628786280.219197378
406106.332554638 788317.02475293406772.999221414790389.941419616
406999.561721295793023.187947378407581.158943534794038.812947378
#Sta/Elev= 30
7914.412 10.43168108.9895.3918698373.9447.9250588951.3663.6761639110.5967.753276
9832.0661.64646610012.061.76089410042.328.96017310941.02 5.4762615377.077.356255
15613.156.55443315663.911.00750515714.097.82157316778.014.29093117922.228.573753
17952.332.41953918012.550.71420618042.66 1.4763218072.779.61608718112.925.182638
18433.622.40588419159.619.42338319171.1314.1453419182.66 25.063919198.2228.69584
19228.7550.2390419258.59 60.316719318.9669.9948219332.4677.3730619452.0978.10001
#Mann= 3 , 0 , 0
7914.412  0.0225       07914.412  0.0225       019452.09  0.0225       0
#XS Ineff= 2 , 0
       09878.549        10065.71       0
Bank Sta=7914.412,19452.09
Exp/Cntr=0.3,0.1

Type RM Length L Ch R = 3 ,  73.624,,,
BEGIN DESCRIPTION:
END DESCRIPTION:
Bridge Culvert--1,0,-1,-1, 0
Deck Dist Width WeirC Skew NumUp NumDn MinLoCord MaxHiCord MaxSubmerge Is_Ogee
47.119950,48.556300,2.6,0, 60, 60, , , 0.95, 0, 0,0,,
 9125.39 9145.05 9157.15 9181.34 9193.43 9203.02 9238.57 9256.35 9266.00 9278.10
 9291.91 9327.46 9383.35 9394.59 9473.26 9585.66 9596.90 9610.26 9619.37 9632.17
 9641.85 9654.08 9664.33 9675.98 9686.81 9698.05 9709.29 9720.53 9731.77 9743.01
 9754.24 9765.48 9776.72 9787.96 9799.20 9810.44 9821.68 9832.92 9844.16 9855.40
 9866.64 9889.12 9894.20 9894.2010012.6410012.6410068.9410114.1210136.3810147.62
10158.8610170.1010201.7510250.0010296.0610322.8810384.1310407.9210595.5010616.26
    7.00    7.00    6.54    6.49    6.63    7.04    6.62    6.72    6.96    6.87
    7.18    7.44    7.62    7.46    8.05    8.00    8.30    8.28    8.56    8.40
    8.60    8.35    8.63    8.45    8.63    8.52    8.72    8.54    8.77    8.47
    8.72    8.61    8.75    8.56    8.84    8.64    8.89    8.71    8.98    8.83
    8.97    8.82    8.91    8.91    9.00    9.00    8.88    8.98    8.89    8.69
    8.83    8.69    8.72    8.44    8.43    8.21    8.30    8.03    7.63    7.41
 -993.00 -993.00 -993.46 -993.51 -993.37 -992.96 -993.38 -993.28 -993.04 -993.13
 -992.82 -992.56 -992.38 -992.54 -991.95 -992.00 -991.70 -991.72 -991.44 -991.60
 -991.40 -991.65 -991.37 -991.55 -991.37 -991.48 -991.28 -991.46 -991.23 -991.53
 -991.28 -991.39 -991.25 -991.44 -991.16 -991.36 -991.11 -991.29 -991.02 -991.17
 -991.03 -991.18 -991.09    6.41    6.50 -991.00 -991.12 -991.02 -991.11 -991.31
 -991.17 -991.31 -991.28 -991.56 -991.57 -991.79 -991.70 -991.97 -992.37 -992.59
 9125.39 9145.05 9157.15 9181.34 9193.43 9203.02 9238.57 9256.35 9266.00 9278.10
 9291.91 9327.46 9383.35 9394.59 9473.26 9585.66 9596.90 9610.26 9619.37 9632.17
 9641.85 9654.08 9664.33 9675.98 9686.81 9698.05 9709.29 9720.53 9731.77 9743.01
 9754.24 9765.48 9776.72 9787.96 9799.20 9810.44 9821.68 9832.92 9844.16 9855.40
 9877.88 9889.12 9899.36 9925.79 9925.7910044.2310044.2310068.9410114.1210147.62
10158.8610170.1010201.7510250.0010296.0610322.8810384.1310407.9210595.5010616.26
    7.00    7.00    6.54    6.49    6.63    7.04    6.62    6.72    6.96    6.87
    7.18    7.44    7.62    7.46    8.05    8.00    8.30    8.28    8.56    8.40
    8.60    8.35    8.63    8.45    8.63    8.52    8.72    8.54    8.77    8.47
    8.72    8.61    8.75    8.56    8.84    8.64    8.89    8.71    8.98    8.83
    8.97    8.82    8.99    8.99    8.99    9.01    9.01    8.88    8.98    8.69
    8.83    8.69    8.72    8.44    8.43    8.21    8.30    8.03    7.63    7.41
 -993.00 -993.00 -993.46 -993.51 -993.37 -992.96 -993.38 -993.28 -993.04 -993.13
 -992.82 -992.56 -992.38 -992.54 -991.95 -992.00 -991.70 -991.72 -991.44 -991.60
 -991.40 -991.65 -991.37 -991.55 -991.37 -991.48 -991.28 -991.46 -991.23 -991.53
 -991.28 -991.39 -991.25 -991.44 -991.16 -991.36 -991.11 -991.29 -991.02 -991.17
 -991.03 -991.18 -991.01 -991.01    6.49    6.51 -990.99 -991.12 -991.02 -991.31
 -991.17 -991.31 -991.28 -991.56 -991.57 -991.79 -991.70 -991.97 -992.37 -992.59
Pier Skew, UpSta & Num, DnSta & Num=  ,9933.18, 2 ,9964.77, 2 , 0 , 0 , 0 ,,
    3.00    3.00
 -991.01    8.99
    3.00    3.00
 -991.00    9.00
Pier Skew, UpSta & Num, DnSta & Num=  ,9973.66, 2 ,10005.25, 2 , 0 , 0 , 0 ,,
    3.00    3.00
 -991.00    9.00
    3.00    3.00
 -991.00    9.00
BR Coef=-1 , 0 , 0 ,, 0 ,,,0.8,0,1,0,
WSPro=,,,, 1 ,,,, 0 ,,,, 0 ,,,,-1 ,-1 ,-1 , 0 , 0 , 0 , 0 , 0
BC Design=,, 0 ,, 0 ,,,,,,

Type RM Length L Ch R = 1 , 22.9682,22.968200,22.968200,22.968200
XS GIS Cut Line= 6
402175.507370919784602.831511065404533.936721474 786337.72787793
405630.869591862787693.413641825406426.645054787 789535.77475293
406739.145054638793005.826836258407416.228387952794195.062947378
#Sta/Elev= 30
7950.5949.5632628865.5823.0378079459.5278.6949939481.9064.9722239884.7195.812989
9996.612 1.7542710169.514.42304410205.8210.7416211218.115.43055811306.379.893335
11330.395.42532211461.743.93455814302.278.156867 14515.34.10957115403.41 6.26771
15585.481.11544715675.687.62219117359.422.74797717660.084.448842 17800.410.27643
17820.441.65492717860.530.68586717920.667.29706117940.713.00931618040.932.466626
19140.678.09316319295.6720.4613119376.5266.5978319428.3578.8168219520.4876.94423
#Mann= 3 , 0 , 0
7950.594   0.013       07950.594   0.013       019520.48   0.013       0
#XS Ineff= 2 , 0
       09901.554        10072.26       0
Bank Sta=7950.594,19520.48
Exp/Cntr=0.3,0.1

Type RM Length L Ch R = 1 ,      -0,0.000000,0.000000,0.000000
XS GIS Cut Line= 6
402091.559164912784695.098582849404000.950610369786037.380655706
  405598.1728324 787890.67926684406218.311721295789668.240030721
406496.089499086792832.215725169407364.145054638794290.549058497
#Sta/Elev= 30
7949.731 5.309169471.5228.91697310013.771.81403610217.529.27398911087.813.851555
14168.636.36849414417.412.13082315009.836.32338615030.082.37015915323.735.845961
15464.941.81445915675.386.16282616737.63 4.8606216787.7311.6526416837.845.293636
17068.3311.6398117328.884.31863417439.1111.8333917479.19 4.84749 17669.67.459192
17689.642.06565817769.810.97675317809.897.249017   178322.632814 18856.14.639988
 19228.512.4886719286.6925.52399 19321.640.9355419379.7977.9663919514.26 77.7089
#Mann= 3 , 0 , 0
7949.731   0.013       07949.731   0.013       019514.26   0.013       0
#XS Ineff= 2 , 0
       09903.518        10068.72       0
Bank Sta=7949.731,19514.26
Exp/Cntr=0.3,0.1